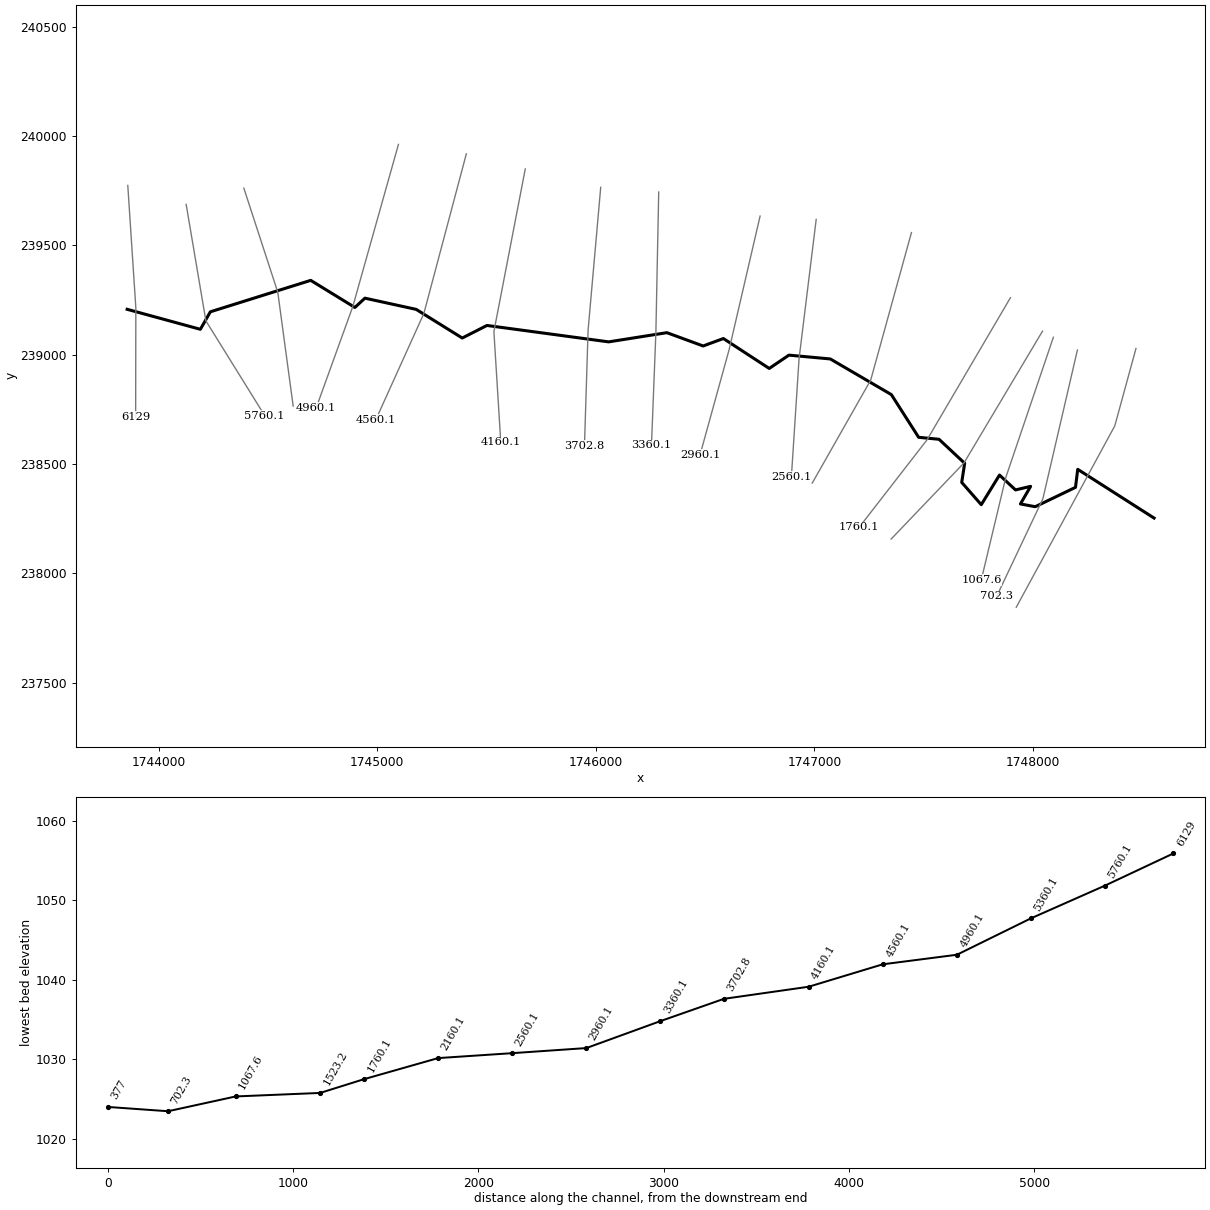
--- RotngCrT1.prj (project) ---

Proj Title=RotngCrT1
Current Plan=p01
Geom File=g01
Flow File=f01
Plan File=p01
DSS Export Rating Curves=0
DSS Export Rating Curve Sorted=0
DSS Export Volume Flow Curves=0
DXF OffsetX=0
DXF OffsetY=0
DXF ScaleX=0
DXF ScaleY=0

--- RotngCrT1.p01 (plan) ---

Plan Title=Floodplain
Program Version=4.00
Geom File=g01
Flow File=f01
K Sum by GR=0
Std Step Tol=0.01
Critical Tol=0.01
Num of Std Step Trials=20
Max Error Tol=0.3
Flow Tol Ratio=0.001
Split Flow NTrial=30
Split Flow Tol=0.02
Split Flow Ratio=0.02
Log Output Level=0
Friction Slope Method=1
Unsteady Friction Slope Method=2
Unsteady Bridges Friction Slope Method=1
Global Log Level=0
CheckData=False
Run HTab=0
Run UNet=0
Run PostProcess=0
UNET Theta=0
UNET Theta Warmup=0
UNET ZTol=0
UNET ZSATol=0
UNET MxIter=0
UNET MaxInSteps=0
UNET DtIC=0
UNET DtMin=0
UNET MaxCRTS=0
UNET WFStab=0
UNET SFStab=0
UNET WFX=0
UNET SFX=0
UNET DSS MLevel=0
UNET DZMax Abort=0
UNET Convert EG Bridges=0
UNET Use Existing IB Tables=0
UNET Froude Limit=0
UNET Froude Power=0
Write IC File=0
Echo Input=False
Echo Output=False
Write Detailed=0

--- RotngCrT1.f01 (steady flow) ---

Flow Title=NFF Regression Equation
Program Version=4.00
Number of Profiles=1
Profile Names=P100yr
River Rch & RM=RotngCrT1,Main      ,6129
730.5429
River Rch & RM=RotngCrT1,Main      ,702.3
911.3237
River Rch & RM=RotngCrT1,Main      ,377
918.6190
Boundary for River Rch & Prof#=RotngCrT1,Main      ,1
Up Type=0
Dn Type=3
Dn Slope=0.003195

--- RotngCrT1.g01 (geometry) ---

Geom Title=USGS 3m DEM
Program Version=4.00

River Reach=RotngCrT1     ,Main
Reach XY= 30
     1743856.402      239207.170     1744191.265      239115.687
     1744236.996      239195.732     1744696.044      239339.529
     1744898.042      239215.574     1744943.952      239258.086
     1745178.376      239206.811     1745389.013      239075.792
     1745501.982      239133.283     1746058.676      239058.203
     1746324.892      239100.297     1746490.827      239039.381
     1746583.385      239073.475     1746793.078      238936.647
     1746883.123      238997.529     1747072.417      238980.085
     1747351.633      238816.998     1747476.424      238621.733
     1747569.689      238612.660     1747686.954      238502.964
     1747673.442      238415.527     1747762.790      238313.571
     1747846.226      238449.030     1747919.546      238381.062
     1747988.647      238397.439     1747941.933      238316.903
     1748009.673      238304.316     1748193.860      238392.913
     1748203.955      238475.284     1748553.179      238252.349

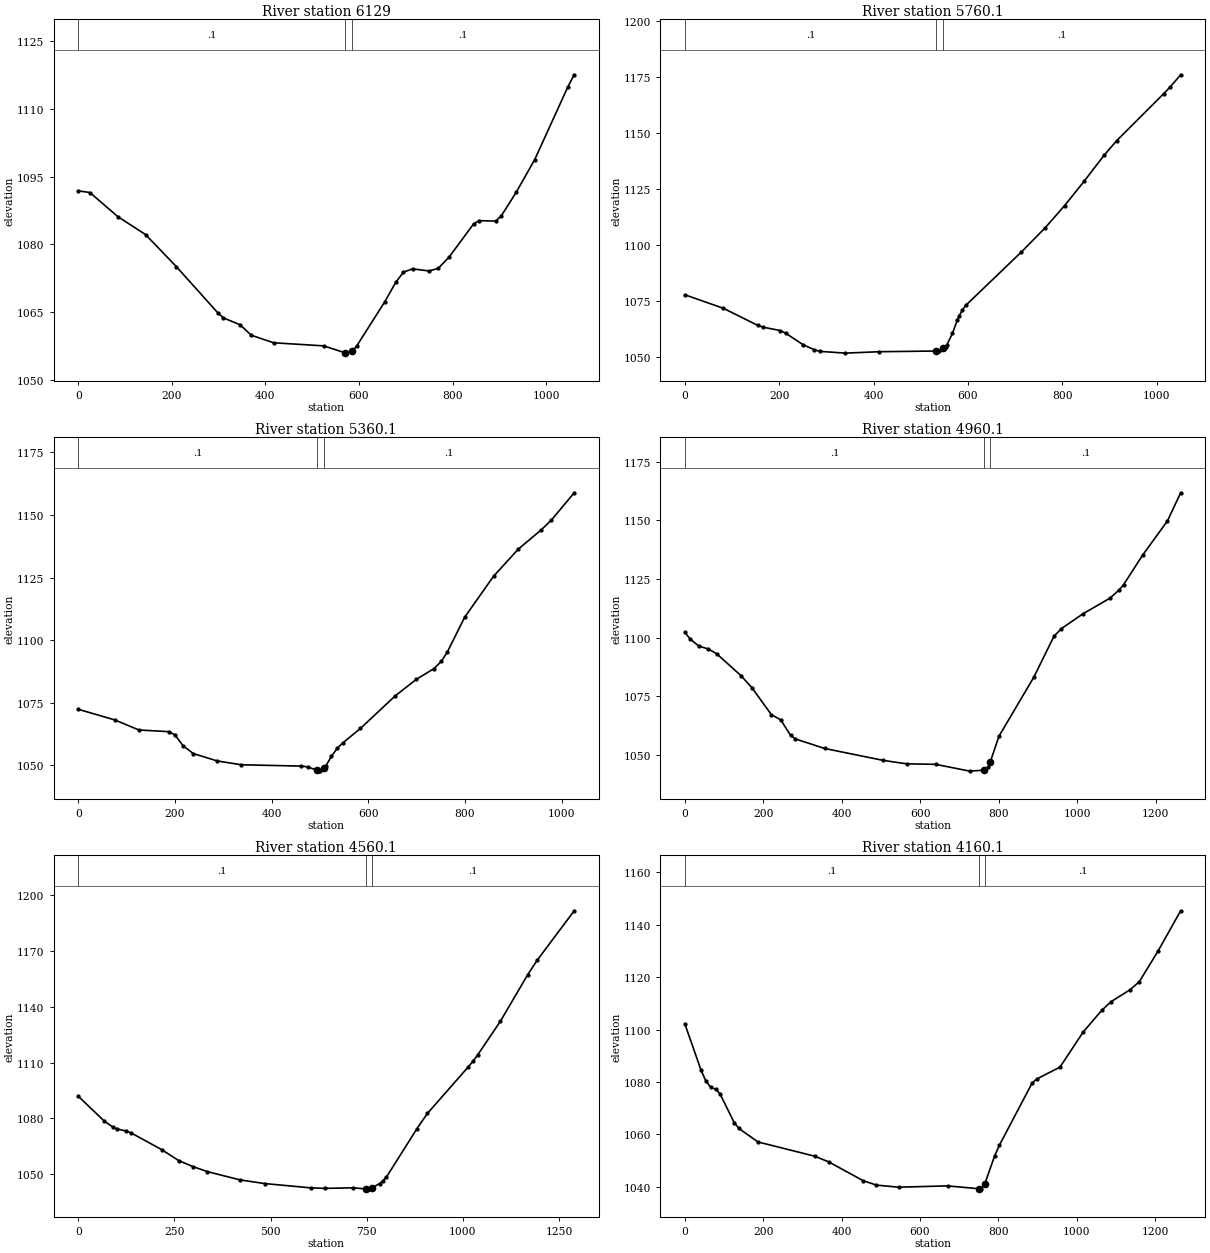
Type RM Length L Ch R = 1 ,6129,382.698,368.903,376.478
XS GIS Cut Line= 3
     1743859.395      239773.681     1743896.188      239213.945
     1743895.294      238714.893
#Sta/Elev= 30
       0 1091.86    24.6 1091.49    84.1 1086.17   143.6 1082.17   209.7 1075.04
   298.3 1064.79   310.3 1063.68   345.9 1062.15   369.7 1059.84   417.3 1058.17
   524.4 1057.48   570.4 1055.94   571.9 1055.87   585.4 1056.27   595.7 1057.55
   655.0 1067.24   678.8 1071.61   695.1 1073.82   714.4 1074.56   750.0 1074.09
   769.5 1074.68   793.3 1077.26   845.0 1084.53   856.9 1085.25   892.5 1085.15
   904.4 1086.34   936.0 1091.52   975.6 1098.77  1046.8 1114.98  1060.0 1117.59
#Mann= 3 , 0 , 0
       0     0.1       0   570.4   0.045       0   585.4     0.1       0
Bank Sta=   570.4,   585.4
Exp/Cntr=0.3,0.1

Type RM Length L Ch R = 1 ,5760.1,379.882,400,392.101
XS GIS Cut Line= 3
     1744126.301      239687.246     1744216.500      239154.435
     1744485.490      238721.108
#Sta/Elev= 30
       0 1077.83    81.8 1071.80   154.7 1064.17   166.1 1063.38   202.2 1061.91
   214.2 1060.65   250.3 1055.61   274.4 1053.33   286.5 1052.61   340.0 1051.83
   412.1 1052.46   532.9 1052.77   539.3 1052.95   547.9 1054.13   553.2 1054.78
   554.6 1055.23   567.1 1060.67   577.1 1066.45   581.1 1068.30   588.2 1071.09
   595.1 1073.08   712.2 1096.72   762.8 1107.53   804.7 1117.59   845.6 1128.31
   888.5 1140.04   914.8 1146.46  1014.3 1167.38  1027.9 1170.34  1050.4 1175.83
#Mann= 3 , 0 , 0
       0     0.1       0   532.9   0.045       0   547.9     0.1       0
Bank Sta=   532.9,   547.9
Exp/Cntr=0.3,0.1

Type RM Length L Ch R = 1 ,5360.1,412.176,400,389.699
XS GIS Cut Line= 3
     1744390.160      239761.245     1744545.373      239285.305
     1744615.767      238764.631
#Sta/Elev= 30
       0 1072.40    75.2 1068.18   125.2 1064.15   187.6 1063.47   200.1 1062.14
   216.8 1057.85   237.6 1054.75   287.5 1051.77   337.5 1050.25   461.7 1049.72
   474.8 1049.39   493.1 1048.09   499.8 1047.71   508.1 1048.99   511.8 1049.71
   523.8 1053.63   535.8 1056.86   547.8 1059.06   583.7 1064.76   655.6 1077.76
   699.7 1084.41   736.2 1088.69   751.4 1091.63   763.4 1095.23   799.4 1109.18
   859.3 1125.58   910.8 1136.47   957.9 1144.08   979.1 1148.05  1026.0 1158.88
#Mann= 3 , 0 , 0
       0     0.1       0   493.1   0.045       0   508.1     0.1       0
Bank Sta=   493.1,   508.1
Exp/Cntr=0.3,0.1

Type RM Length L Ch R = 1 ,4960.1,399.476,400,392.716
XS GIS Cut Line= 3
     1745097.226      239961.296     1744888.301      239219.197
     1744720.794      238755.809
#Sta/Elev= 30
       0 1102.28    13.7 1099.47    35.4 1096.46    60.1 1095.20    81.1 1093.18
   142.9 1083.89   171.1 1078.69   220.4 1067.27   244.7 1064.96   269.8 1058.33
   282.1 1056.84   356.1 1052.80   506.0 1047.70   565.8 1046.24   639.3 1046.03
   726.1 1043.13   763.4 1043.55   773.9 1044.99   778.4 1047.00   800.8 1058.04
   889.2 1083.08   940.8 1100.60   959.4 1103.84  1015.0 1110.23  1083.6 1116.87
  1107.7 1120.48  1118.6 1122.69  1167.0 1135.26  1230.1 1149.79  1263.7 1161.79
#Mann= 3 , 0 , 0
       0     0.1       0   763.4   0.045       0   778.4     0.1       0
Bank Sta=   763.4,   778.4
Exp/Cntr=0.3,0.1

Type RM Length L Ch R = 1 ,4560.1,396.624,400,409.961
XS GIS Cut Line= 3
     1745407.762      239918.166     1745213.653      239188.466
     1744993.515      238701.590
#Sta/Elev= 30
       0 1091.84    67.4 1078.53    88.9 1075.42   101.2 1074.22   125.0 1073.19
   138.1 1072.06   217.4 1063.10   260.9 1057.28   297.8 1054.06   334.7 1051.40
   420.7 1046.88   484.7 1044.92   604.9 1042.60   641.8 1042.33   715.5 1042.65
   747.6 1042.02   756.3 1041.93   762.6 1042.37   783.2 1044.93   791.3 1046.27
   801.2 1048.42   880.6 1074.45   907.8 1082.64  1012.8 1107.36  1025.8 1110.56
  1038.9 1114.23  1097.3 1132.12  1168.8 1157.31  1193.2 1164.99  1289.4 1191.58
#Mann= 3 , 0 , 0
       0     0.1       0   747.6   0.045       0   762.6     0.1       0
Bank Sta=   747.6,   762.6
Exp/Cntr=0.3,0.1

Type RM Length L Ch R = 1 ,4160.1,458.205,457.291,451.26
XS GIS Cut Line= 3
     1745677.324      239849.158     1745533.814      239105.343
     1745565.286      238598.951
#Sta/Elev= 30
       0 1102.19    41.4 1084.51    53.5 1080.46    65.6 1078.04    79.4 1077.14
    89.6 1075.51   126.1 1064.48   138.2 1062.25   186.5 1057.11   331.6 1051.67
   367.9 1049.45   454.5 1042.37   488.8 1040.64   545.7 1039.85   670.2 1040.35
     750 1039.26   754.9 1039.11     765 1040.98   790.6 1051.87   802.5 1055.85
   885.7 1079.49   897.6 1081.11   957.1 1085.66  1016.6 1099.11  1064.2 1107.41
  1088.0 1110.68  1135.6 1115.15  1159.3 1118.21  1206.9 1129.83  1264.9 1145.29
#Mann= 3 , 0 , 0
       0     0.1       0     750   0.045       0     765     0.1       0
Bank Sta=     750,     765
Exp/Cntr=0.3,0.1

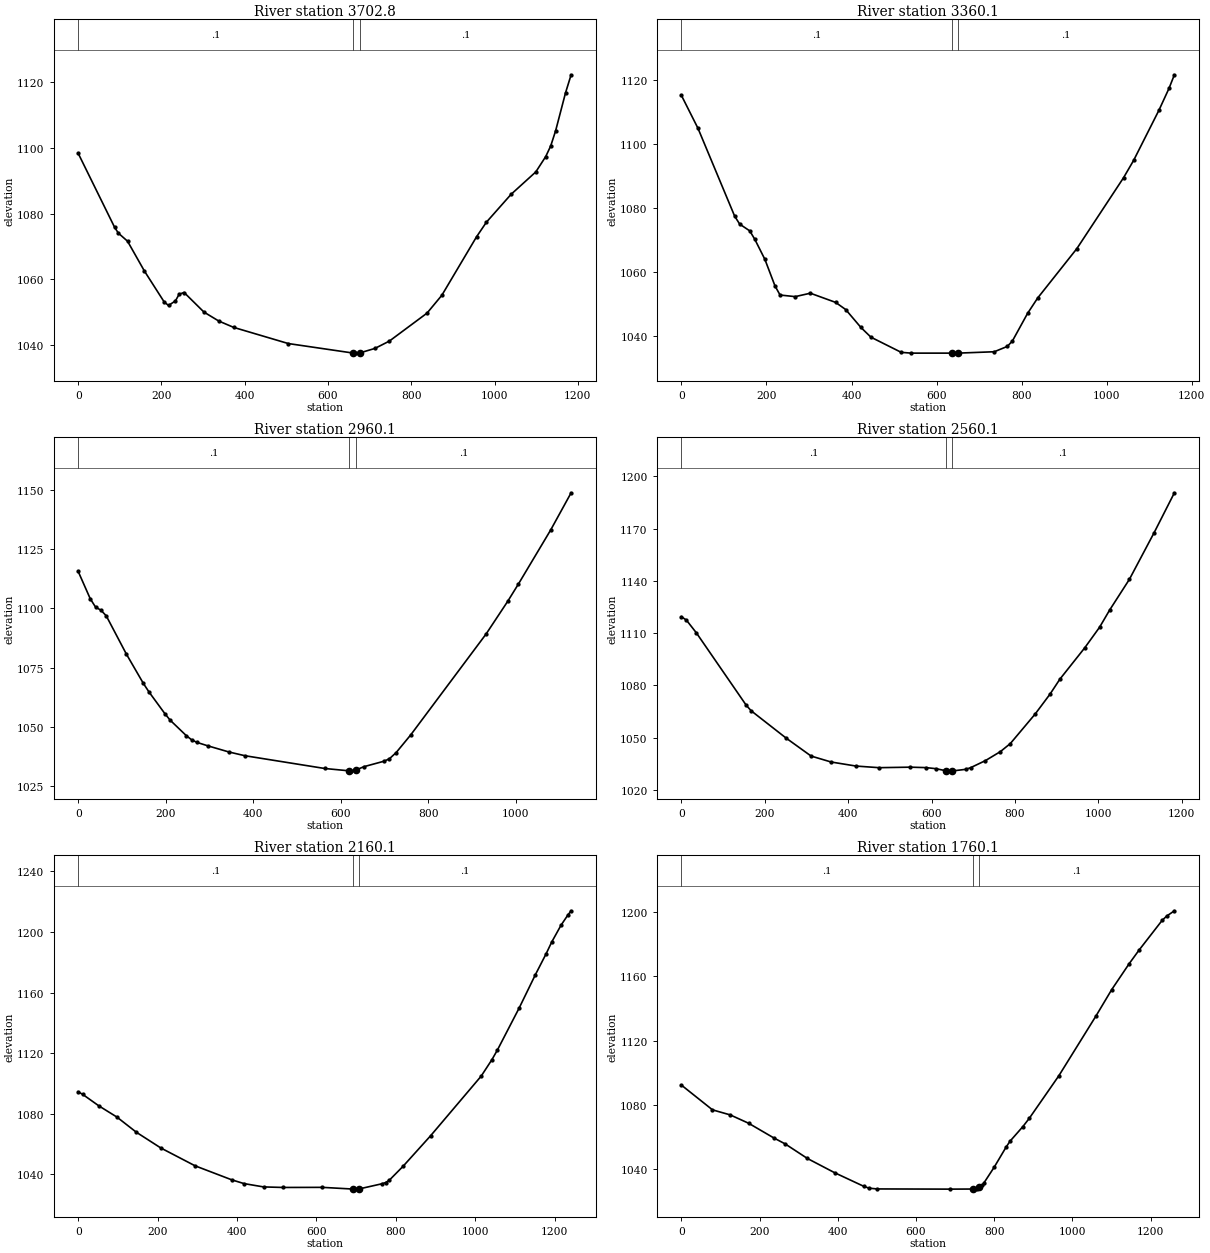
Type RM Length L Ch R = 1 ,3702.8,337.634,342.709,343.647
XS GIS Cut Line= 3
     1746022.364      239765.055     1745964.649      239111.628
     1745948.058      238584.035
#Sta/Elev= 30
       0 1098.36    87.5 1075.85    96.6 1074.07   118.5 1071.64   159.0 1062.57
   206.7 1053.12   217.0 1052.09   233.6 1053.48   242.5 1055.52   254.4 1056.03
   302.1 1050.07   337.5 1047.36   373.6 1045.41   504.7 1040.50   660.9 1037.60
   664.5 1037.59   675.9 1037.64   712.6 1039.02   747.2 1041.24   837.8 1049.76
   873.4 1055.19   956.6 1072.95   980.3 1077.40  1039.7 1085.90  1099.1 1092.72
  1122.9 1097.39  1134.8 1100.60  1146.6 1105.21  1170.4 1116.76  1183.8 1122.24
#Mann= 3 , 0 , 0
       0     0.1       0   660.9   0.045       0   675.9     0.1       0
Bank Sta=   660.9,   675.9
Exp/Cntr=0.3,0.1

Type RM Length L Ch R = 1 ,3360.1,395.928,400,392.577
XS GIS Cut Line= 3
     1746287.613      239743.490     1746274.668      239101.049
     1746254.451      238584.795
#Sta/Elev= 30
       0 1115.10    38.9 1104.86   125.0 1077.52   136.9 1075.01   160.6 1072.90
   172.5 1070.27   196.3 1063.99   220.0 1055.73   231.9 1052.90   267.5 1052.40
   303.1 1053.47   362.5 1050.61   386.3 1048.37   421.9 1042.81   445.6 1039.76
   516.9 1035.03   540.6 1034.79   635.1 1034.79   650.1 1034.79   735.6 1035.22
   766.3 1036.88   778.2 1038.55   813.9 1047.16   837.6 1051.95   930.0 1067.39
  1039.6 1089.45  1063.4 1094.87  1122.8 1110.47  1146.6 1117.32  1159.2 1121.54
#Mann= 3 , 0 , 0
       0     0.1       0   635.1   0.045       0   650.1     0.1       0
Bank Sta=   635.1,   650.1
Exp/Cntr=0.3,0.1

Type RM Length L Ch R = 1 ,2960.1,403.647,400,405.281
XS GIS Cut Line= 3
     1746751.261      239633.508     1746609.757      239023.112
     1746476.429      238540.752
#Sta/Elev= 30
       0 1115.58    27.6 1104.05    39.8 1100.52    52.0 1099.24    64.2 1096.85
   110.1 1080.76   149.1 1068.35   161.7 1064.82   198.2 1055.62   210.4 1052.86
   247.0 1046.39   259.2 1044.62   271.3 1043.53   295.7 1042.10   344.5 1039.48
   381.0 1037.90   563.8 1032.51   619.1 1031.53   623.8 1031.40   634.1 1031.81
   653.6 1033.29   698.7 1035.55   711.5 1036.59   727.1 1039.24   760.3 1046.67
   932.7 1089.22   982.0 1102.96  1006.6 1110.29  1080.5 1133.11  1127.0 1148.71
#Mann= 3 , 0 , 0
       0     0.1       0   619.1   0.045       0   634.1     0.1       0
Bank Sta=   619.1,   634.1
Exp/Cntr=0.3,0.1

Type RM Length L Ch R = 1 ,2560.1,383.167,400,388.978
XS GIS Cut Line= 3
     1747007.884      239618.413     1746929.495      238981.376
     1746894.496      238442.077
#Sta/Elev= 30
       0 1119.36    11.9 1117.42    35.8 1110.11   155.4 1068.55   167.4 1065.35
   251.1 1049.70   310.9 1039.41   358.8 1036.00   418.6 1033.67   473.7 1032.74
   548.3 1033.03   586.1 1032.78   610.0 1032.18   634.3 1030.97   645.8 1030.76
   649.3 1030.85   681.5 1031.78   693.4 1032.73   729.1 1036.81   764.8 1041.95
   788.6 1046.55   848.1 1063.48   883.8 1074.92   907.6 1083.56   967.1 1101.51
  1002.8 1113.36  1026.6 1123.10  1074.2 1140.82  1133.7 1167.68  1182.1 1190.48
#Mann= 3 , 0 , 0
       0     0.1       0   634.3   0.045       0   649.3     0.1       0
Bank Sta=   634.3,   649.3
Exp/Cntr=0.3,0.1

Type RM Length L Ch R = 1 ,2160.1,409.181,400,393.392
XS GIS Cut Line= 3
     1747443.497      239558.031     1747257.263      238883.581
     1746989.716      238412.307
#Sta/Elev= 30
       0 1094.41    11.2 1092.75    52.2 1085.11    97.4 1077.76   146.7 1067.68
   208.2 1057.31   294.5 1045.53   386.8 1036.28   417.6 1033.80   466.9 1031.60
   516.2 1031.24   614.7 1031.31   692.2 1030.18   695.7 1030.14   707.2 1030.25
   765.7 1033.71   774.4 1034.50   783.5 1035.98   818.0 1045.13   887.7 1065.39
  1015.1 1104.78  1042.4 1115.75  1056.0 1122.03  1110.6 1149.68  1151.6 1171.75
  1178.9 1185.70  1192.8 1193.35  1216.4 1204.53  1233.5 1211.18  1241.6 1213.95
#Mann= 3 , 0 , 0
       0     0.1       0   692.2   0.045       0   707.2     0.1       0
Bank Sta=   692.2,   707.2
Exp/Cntr=0.3,0.1

Type RM Length L Ch R = 1 ,1760.1,236.068,236.916,234.848
XS GIS Cut Line= 3
     1747896.362      239260.434     1747515.096      238610.582
     1747204.037      238209.552
#Sta/Elev= 30
       0 1092.29    79.4 1076.89   124.7 1073.75   171.6 1068.57   235.6 1059.49
   265.5 1055.64   322.3 1046.58   391.7 1037.74   465.8 1029.31   479.6 1028.10
   500.1 1027.61   687.8 1027.49   745.9 1027.55   755.0 1027.71   760.9 1028.61
   770.1 1030.09   773.0 1031.06   800.1 1041.17   830.2 1053.55   840.7 1057.39
   873.6 1066.50   890.3 1071.77   965.4 1098.11  1060.7 1135.49  1100.6 1151.78
  1145.7 1168.08  1170.7 1176.45  1229.9 1195.01  1241.6 1197.69  1261.0 1200.91
#Mann= 3 , 0 , 0
       0     0.1       0   745.9   0.045       0   760.9     0.1       0
Bank Sta=   745.9,   760.9
Exp/Cntr=0.3,0.1

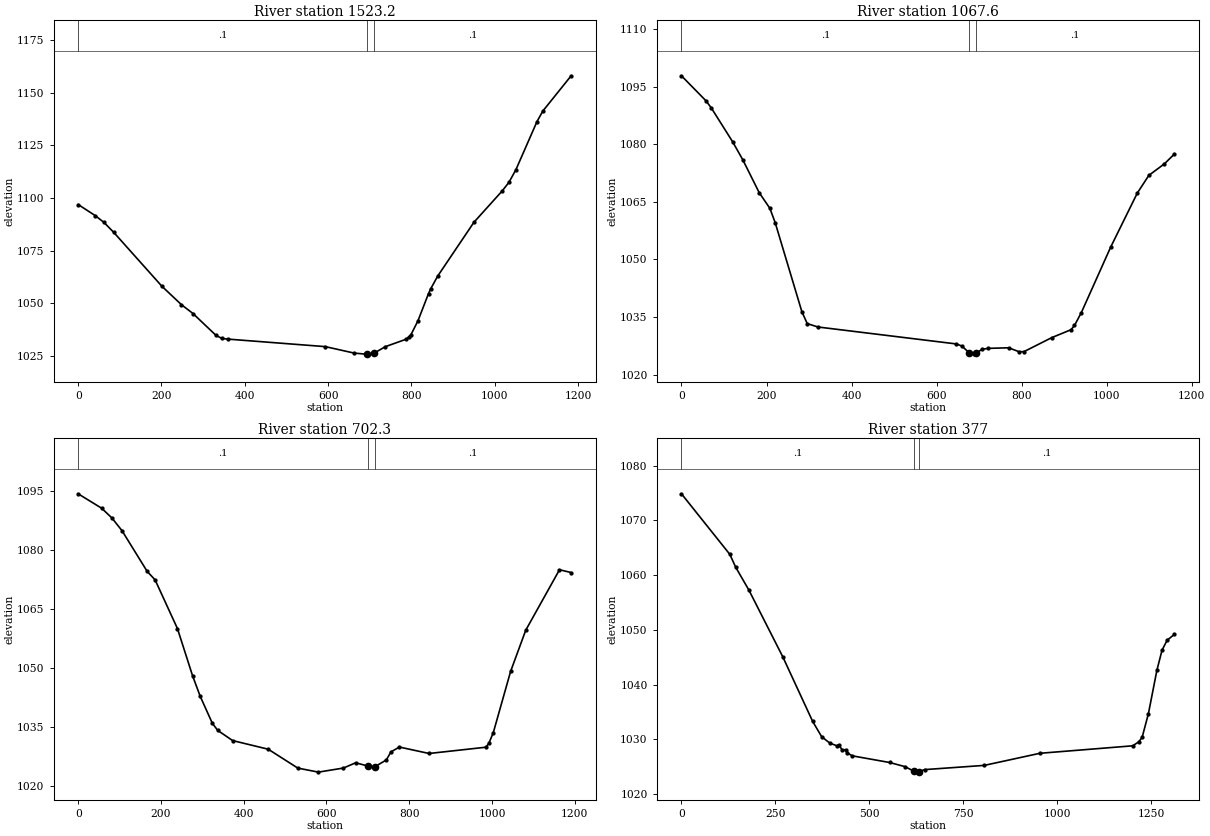
Type RM Length L Ch R = 1 ,1523.2,445.147,455.58,457.99
XS GIS Cut Line= 3
     1748043.004      239107.323     1747683.917      238504.619
     1747350.726      238156.497
#Sta/Elev= 30
       0 1096.86    40.7 1091.63    61.8 1088.38    85.0 1083.71   201.0 1058.01
   248.0 1049.24   275.6 1045.06   330.9 1034.66   344.7 1033.25   358.6 1032.91
   593.5 1029.32   662.6 1026.25   690.2 1025.76     694 1025.78     709 1026.07
   737.4 1029.31   786.7 1032.80   794.6 1033.88   799.0 1035.03   815.8 1041.65
   841.0 1054.52   846.2 1056.78   863.3 1062.92   950.1 1088.44  1017.9 1103.32
  1034.1 1107.41  1050.9 1113.45  1101.3 1136.23  1115.4 1141.28  1183.4 1158.04
#Mann= 3 , 0 , 0
       0     0.1       0     694   0.045       0     709     0.1       0
Bank Sta=     694,     709
Exp/Cntr=0.3,0.1

Type RM Length L Ch R = 1 ,1067.6,337.911,365.269,267.316
XS GIS Cut Line= 3
     1748092.603      239079.288     1747874.956      238437.828
     1747762.807      237969.184
#Sta/Elev= 30
       0 1097.82    57.5 1091.33    70.0 1089.48   120.2 1080.66   144.4 1075.91
   182.8 1067.38   207.9 1063.30   220.5 1059.53   283.1 1036.39   295.7 1033.28
   320.8 1032.39   646.7 1027.97   659.2 1027.44   676.7 1025.68   687.9 1025.32
   691.7 1025.58   707.6 1026.57   720.8 1026.82   769.6 1026.97   794.0 1025.94
   805.5 1025.97   870.7 1029.61   916.1 1031.68   924.3 1032.78   940.5 1036.16
  1009.5 1053.22  1072.1 1067.29  1099.2 1071.89  1135.8 1074.90  1159.3 1077.45
#Mann= 3 , 0 , 0
       0     0.1       0   676.7   0.045       0   691.7     0.1       0
Bank Sta=   676.7,   691.7
Exp/Cntr=0.3,0.1

Type RM Length L Ch R = 1 ,702.3,320.298,325.31,352.106
XS GIS Cut Line= 3
     1748202.585      239021.063     1748044.678      238340.764
     1747833.823      237895.370
#Sta/Elev= 30
       0 1094.39    56.7 1090.72    81.4 1088.25   105.8 1085.01   166.7 1074.62
   185.8 1072.47   239.9 1060.04   276.4 1048.02   294.8 1042.80   324.3 1035.88
   337.4 1034.08   373.2 1031.50   459.2 1029.30   530.7 1024.49   580.5 1023.46
   640.9 1024.50   670.5 1025.84   701.3 1024.98   716.3 1024.80   744.6 1026.56
   755.9 1028.63   776.3 1029.85   847.9 1028.21   985.3 1029.81   992.4 1030.80
  1003.2 1033.55  1044.9 1049.11  1081.5 1059.62  1163.1 1075.04  1191.2 1074.33
#Mann= 3 , 0 , 0
       0     0.1       0   701.3   0.045       0   716.3     0.1       0
Bank Sta=   701.3,   716.3
Exp/Cntr=0.3,0.1

Type RM Length L Ch R = 1 ,377,375.665,377.008,378.494
XS GIS Cut Line= 3
     1748470.435      239027.861     1748373.555      238674.041
     1747922.856      237844.248
#Sta/Elev= 30
       0 1074.85   128.6 1063.79   144.2 1061.44   179.4 1057.25   269.8 1045.02
   348.9 1033.27   372.9 1030.47   394.8 1029.29   413.5 1028.81   419.0 1028.99
   427.0 1028.07   436.5 1028.09   440.5 1027.55   453.9 1026.98   553.6 1025.76
   594.1 1025.01   617.8 1024.19   628.2 1024.00   632.8 1024.11   646.6 1024.46
   805.3 1025.23   953.1 1027.44  1200.3 1028.81  1215.7 1029.51  1225.2 1030.34
  1242.0 1034.70  1264.6 1042.64  1278.2 1046.28  1291.7 1048.10  1311.1 1049.17
#Mann= 3 , 0 , 0
       0     0.1       0   617.8   0.045       0   632.8     0.1       0
Bank Sta=   617.8,   632.8
Exp/Cntr=0.3,0.1